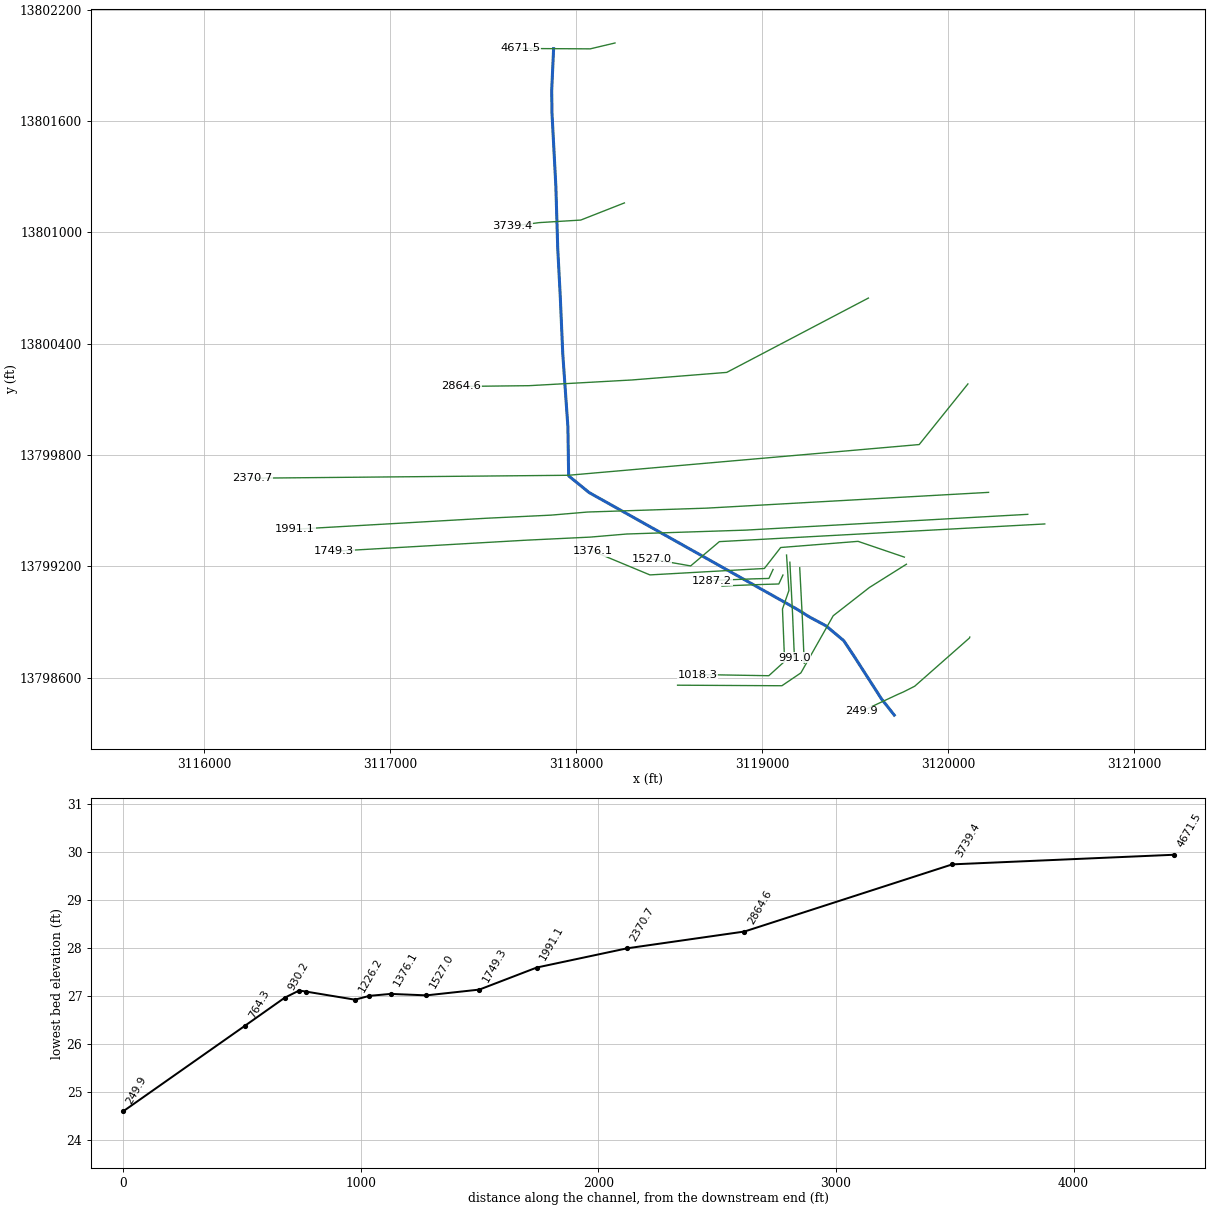
--- C132-00-00.PRJ (project) ---

Proj Title=C132-00-00
Current Plan=p02
Default Exp/Contr=0.3,0.1
English Units
Geom File=g01
Flow File=f01
Flow File=f02
Plan File=p01
Plan File=p02
Y Axis Title=Elevation
X Axis Title(PF)=Main Channel Distance
X Axis Title(XS)=Station
BEGIN DESCRIPTION:
Sims Bayou Watershed
Tributary 13.83 to Sims Bayou
HCFCD Unit C132-00-00
Flood Hazard Model
10, 2, 1, 0.2% Event
Filename C132-00-00.prj
Prepared by:  Watershed Concepts  Date:
Reviewed by:                      Date:
STATUS FINAL
END DESCRIPTION:
DSS Export Rating Curves= 0
DSS Export Rating Curve Sorted= 0
DSS Export Volume Flow Curves= 0
DXF OffsetX= 0
DXF OffsetY= 0
DXF ScaleX= 1
DXF ScaleY= 10

--- C132-00-00.p02 (plan) ---

Plan Title=Effective Floodway 2015
Program Version=4.10
Short Identifier=RiskMAP FW
Geom File=g01
Flow File=f02
Subcritical Flow
K Sum by GR= 0
Std Step Tol= 0.01
Critical Tol= 0.01
Num of Std Step Trials= 20
Max Error Tol= 0.3
Flow Tol Ratio= 0.001
Split Flow NTrial= 30
Split Flow Tol= 0.02
Split Flow Ratio= 0.02
Log Output Level= 0
Friction Slope Method= 1
Unsteady Friction Slope Method= 2
Unsteady Bridges Friction Slope Method= 1
Parabolic Critical Depth
Global Vel Dist= 0 , 0 , 0
Global Log Level= 0
CheckData=True
Encroach Param=-1 ,0,0, 2
Encroach River=C132-00-00
Encroach Reach=Reach - 1
Encroach Node=4671.5
       1  4945.1  5031.6
Encroach Node=3739.4
       1  4943.6  5030.8
Encroach Node=2864.6
       1  4948.8  5033.1
Encroach Node=2370.7
       1  4948.8  5033.1
Encroach Node=1991.1
       1 4985.86 5046.69
Encroach Node=1870.2
       1 4985.86 5046.69
Encroach Node=1749.3
       1 4985.86 5046.69
Encroach Node=1527.0
       1  4973.3  5023.3
Encroach Node=1376.1
       1 4984.78 5029.81
Encroach Node=1287.2
       1 4984.78 5029.81
Encroach Node=1256.7
       1 4984.78 5029.81
Encroach Node=1226.2
       1 4984.78 5029.81
Encroach Node=1018.3
       1 4964.05 5012.18
Encroach Node=991.0
       1 4964.05 5012.18
Encroach Node=960.6
       1 4964.05 5012.18
Encroach Node=930.2
       1 4964.05 5012.18
Encroach Node=764.3
       1  4958.1  5042.4
Encroach Node=249.9
       1  4965.3  5042.5
Encroach Reach=C132-00-00_0002
Encroach Node=4671.5
       1  4945.1  5031.6
Encroach Node=3739.4
       1  4943.6  5030.8
Encroach Node=2864.6
       1  4948.8  5033.1
Encroach Node=2370.7
       1  4948.8  5033.1
Encroach Node=1991.1
       1 4985.86 5046.69
Encroach Node=1870.2
       1 4985.86 5046.69
Encroach Node=1749.3
       1 4985.86 5046.69
Encroach Node=1527.0
       1  4973.3  5023.3
Encroach Node=1376.1
       1 4984.78 5029.81
Encroach Node=1287.2
       1 4984.78 5029.81
Encroach Node=1256.7
       1 4984.78 5029.81
Encroach Node=1226.2
       1 4984.78 5029.81
Encroach Node=1018.3
       1 4964.05 5012.18
Encroach Node=991.0
       1 4964.05 5012.18
Encroach Node=960.6
       1 4964.05 5012.18
Encroach Node=930.2
       1 4964.05 5012.18
Encroach Node=764.3
       1  4958.1  5042.4
Encroach Node=249.9
       1  4965.3  5042.5
BEGIN DESCRIPTION:
FEMA Effective Risk Map Study Floodway May 02, 2019
END DESCRIPTION:
Computation Interval=1HOUR
Output Interval=1HOUR
Run HTab= 0
Run UNet= 0
Run PostProcess= 0
Run WQNet= 0
UNET Theta= 1
UNET Theta Warmup= 1
UNET ZTol= 0.02
UNET ZSATol= 0.1
UNET MxIter= 20
UNET MaxInSteps= 20
UNET DtIC= 0
UNET DtMin= 0
UNET MaxCRTS= 20
UNET WFStab= 2
UNET SFStab= 1
UNET WFX= 1
UNET SFX= 1
UNET DSS MLevel= 4
UNET DZMax Abort= 100
UNET Convert EG Bridges=-1
UNET Use Existing IB Tables=-1
UNET Froude Reduction=False
UNET Froude Limit= 1
UNET Froude Power= 10
UNET Time Slicing=0,0, 5
UNET Junction Losses=0
Instantaneous Interval=1HOUR
Write IC File= 0
IC Time=0,,
Write IC File at Sim End=0
Echo Input=False
Echo Parameters=False
Echo Output=False
Write Detailed= 0
WQ AD Non Conservative
WQ ULTIMATE=-1
WQ Max Comp Step=1HOUR
WQ Output Interval=15MIN
WQ Output Selected Increments= 0
WQ Output face flow=0
WQ Output face velocity=0
WQ Output face area=0
WQ Output face dispersion=0
WQ Output cell volume=0
WQ Output cell surface area=0
WQ Output cell continuity=0
WQ Output cumulative cell continuity=0
WQ Output face conc=0
WQ Output face dconc_dx=0
WQ Output face courant=0
WQ Output face peclet=0
WQ Output face adv mass=0
WQ Output face disp mass=0
WQ Output cell mass=0
WQ Output cell source sink temp=0
WQ Output cell source sink nsm=0
WQ Output MaxMinRange=-1
WQ Daily Max Min Mean=-1
WQ Daily Range=0
WQ Daily Time=0
WQ Create Restart=0
WQ Fixed Restart=0
WQ System Summary=0
WQ Use Fixed Temperature=0
Sorting and Armoring Iterations= 10
XS Update Threshold= 0.02
Hydraulics Update Threshold= 0.02
Energy Slope Method= 1
Volume Change Method= 0
XS Weighting Method= 0
Number of US Weighted Cross Sections= 1
Number of DS Weighted Cross Sections= 1
Upstream XS Weight=0.25
Main XS Weight=0.5
Downstream XS Weight=0.25
Number of DS XS's Weighted with US Boundary= 1
Upstream Boundary Weight= 1
Weight of XSs Associated with US Boundary= 0
Number of US XS's Weighted with DS Boundary= 1
Downstream Boundary Weight= 0.5
Weight of XSs Associated with DS Boundary= 0.5
Sediment Output Level= 4
Mass or Volume Output= 0
Output Increment Type= 1
Profile and TS Output Increment= 10
XS Output Flag= 0
XS Output Increment= 10
Disregard all LS=0
Disregard all Conn=0
Disregard all Breaches=0
Disregard all Pumps=0

--- C132-00-00.p01 (plan) ---

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Plan Title=Effective Multi-Profile 2015
Short Identifier=RiskMAP MP
Geom File=g01
Flow File=f01
Encroach Param=-1 ,0,0, 0
FEMA Effective Risk Map Study Multi-Profile May 02, 2019
UNET ZSATol= 0.05
UNET MaxInSteps= 0

--- C132-00-00.f02 (steady flow) ---

Flow Title=Effective Floodway 2015
Program Version=4.10
Number of Profiles= 2
Profile Names=1PCT_100yr,Floodway
River Rch & RM=C132-00-00,C132-00-00_0002 ,4671.5
    1032    1032
River Rch & RM=C132-00-00,C132-00-00_0002 ,2370.7
    1223    1223
River Rch & RM=C132-00-00,C132-00-00_0002 ,1256.7
    1245    1245
River Rch & RM=C132-00-00,C132-00-00_0002 ,960.6
    1473    1473
Boundary for River Rch & Prof#=C132-00-00,C132-00-00_0002 , 1
Up Type= 0
Dn Type= 3
Dn Slope=0.0035
Boundary for River Rch & Prof#=C132-00-00,C132-00-00_0002 , 2
Up Type= 0
Dn Type= 1
Dn Known WS=32.31
DSS Import GetInterval= 0
DSS Import GetPeak= 0
DSS Import FillOption= 0

--- C132-00-00.f01 (steady flow) ---

Flow Title=Effective Multi-Profile 2015
Program Version=4.10
Number of Profiles= 6
Profile Names=10PCT_10yr,4PCT_25yr,2PCT_50yr,1PCT_100yr,1PCT_Plus,0.2PCT_500yr
River Rch & RM=C132-00-00,C132-00-00_0002 ,4671.5
     529     695     853    1032    1238    1566
River Rch & RM=C132-00-00,C132-00-00_0002 ,2370.7
     627     823    1012    1223    1468    1858
River Rch & RM=C132-00-00,C132-00-00_0002 ,1256.7
     639     838    1030    1245    1494    1892
River Rch & RM=C132-00-00,C132-00-00_0002 ,960.6
     755     992    1218    1473    1767    2238
Boundary for River Rch & Prof#=C132-00-00,C132-00-00_0002 , 1
Up Type= 0
Dn Type= 3
Dn Slope=0.0035
Boundary for River Rch & Prof#=C132-00-00,C132-00-00_0002 , 2
Up Type= 0
Dn Type= 3
Dn Slope=0.0035
Boundary for River Rch & Prof#=C132-00-00,C132-00-00_0002 , 3
Up Type= 0
Dn Type= 3
Dn Slope=0.0035
Boundary for River Rch & Prof#=C132-00-00,C132-00-00_0002 , 4
Up Type= 0
Dn Type= 3
Dn Slope=0.0035
DSS Import GetInterval= 0
DSS Import GetPeak= 0
DSS Import FillOption= 0

--- C132-00-00.g01 (geometry) ---

Geom Title=C132-00-00 2015
Program Version=4.10

River Reach=C132-00-00      ,C132-00-00_0002
Reach XY= 21
      3117878.41     13801989.46      3117868.08     13801763.49
      3117869.75       13801641.       3117890.5       13801248.
      3117900.75       13800910.      3117914.25       13800654.
      3117927.75       13800344.      3117955.25       13799952.
      3117959.25       13799688.      3117959.25       13799688.
       3118069.5       13799598.      3118511.21     13799350.03
       3118925.5       13799117.       3118925.5       13799117.
      3119188.25       13798969.      3119253.75       13798928.
      3119343.25       13798880.      3119438.75       13798800.
        3119495.       13798715.        3119641.       13798487.
      3119710.18     13798399.05

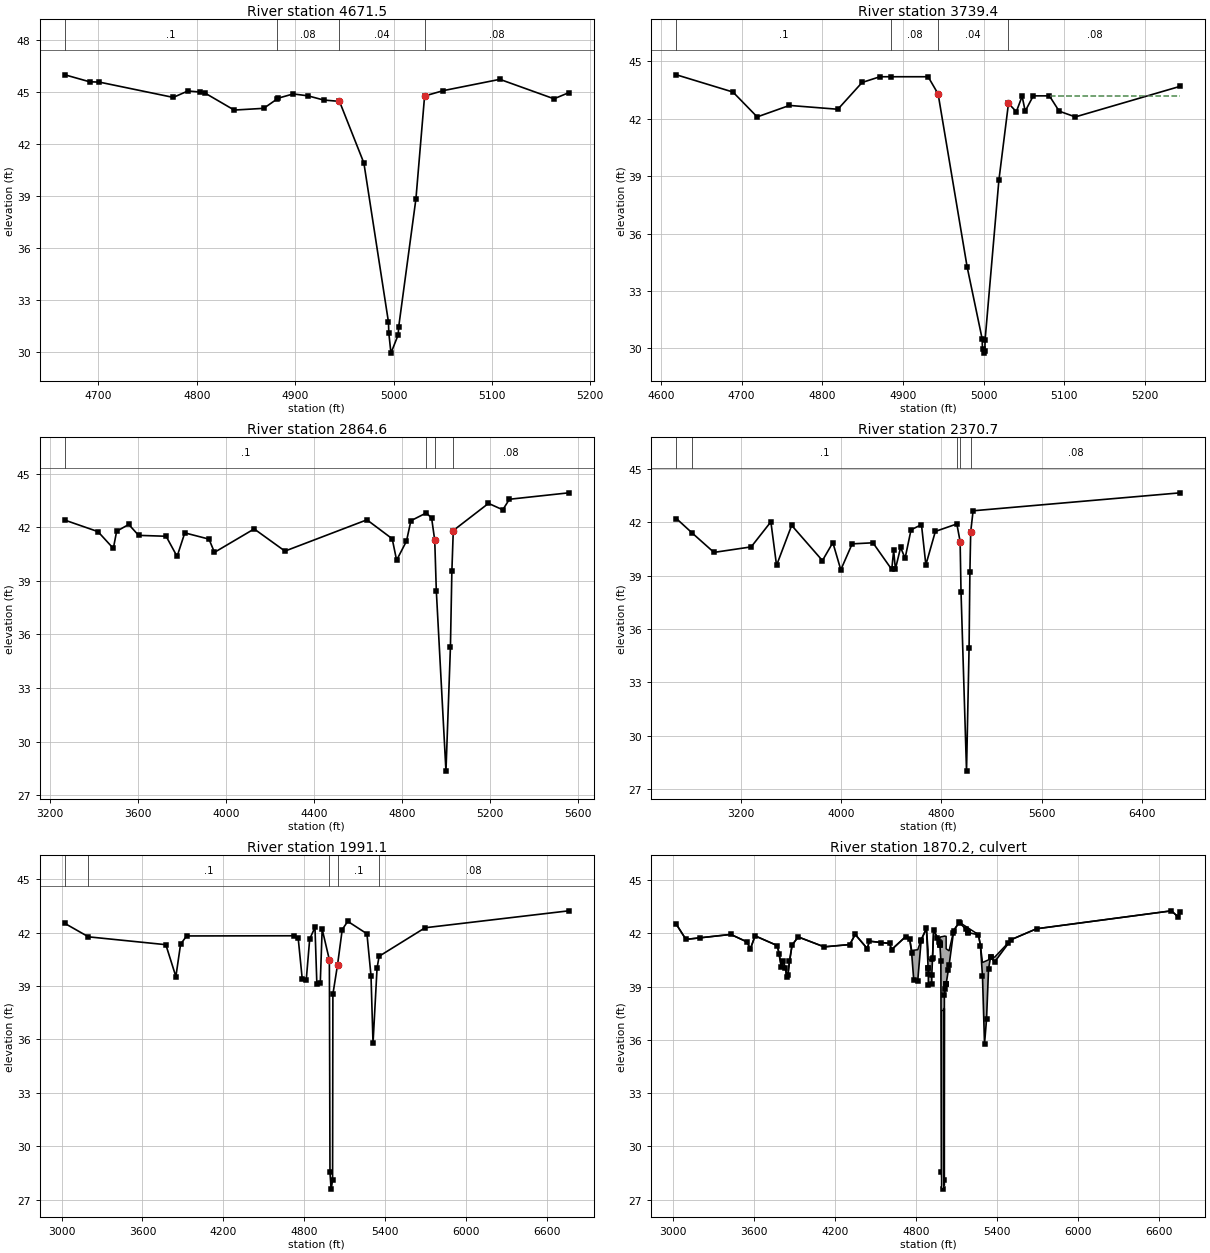
Type RM Length L Ch R = 1 ,4671.5  ,932.1,932.1,932.1
BEGIN DESCRIPTION:
Cross Section 4671.5
END DESCRIPTION:
XS GIS Cut Line= 3
      3118208.57     13802020.06      3118075.23     13801988.43
      3117700.31     13801990.43
#Sta/Elev= 27
  4666.1   45.98  4691.1   45.58  4701.1   45.56  4776.1   44.68  4791.1   45.05
  4803.1   44.99  4808.1   44.94  4838.1   43.95  4868.1   44.05  4881.5   44.58
  4883.1   44.64  4898.1   44.88  4913.1   44.77  4928.9   44.53  4945.1   44.45
  4969.9    40.9  4994.9   31.73  4995.2   31.13  4997.4   29.95  5004.8   31.01
  5005.2   31.43  5022.8   38.84  5031.6   44.76  5050.6   45.07  5108.1   45.72
  5163.1    44.6  5178.1   44.95
#Mann= 4 , 1 , 0
  4666.1      .1       0  4881.5     .08       0  4945.1     .04       0
  5031.6     .08       0
Bank Sta=4945.1,5031.6
XS Rating Curve= 0 ,0
Exp/Cntr=0.3,0.1

Type RM Length L Ch R = 1 ,3739.4  ,1009.5,874.8,874.5
BEGIN DESCRIPTION:
Cross Section 3739.4
END DESCRIPTION:
XS GIS Cut Line= 4
       3118259.1     13801158.41      3118024.47     13801066.07
      3117802.75     13801052.47      3117654.08      13801033.2
#Sta/Elev= 26
  4619.4    44.3  4689.4    43.4  4719.4    42.1  4759.4    42.7  4819.4    42.5
  4849.4    43.9  4871.5    44.2  4884.9    44.2  4931.2    44.2  4943.6    43.3
  4979.5   34.27  4998.1   30.51  4998.6   29.94  5000.1   29.75  5001.5   29.87
  5001.8   30.44  5018.9   38.79  5030.8   42.81  5040.5   42.37  5047.7   43.18
  5051.5    42.4  5061.5    43.2  5081.5    43.2  5093.6    42.4  5113.6    42.1
  5243.6    43.7
#Mann= 4 , 1 , 0
  4619.4      .1       0  4884.9     .08       0  4943.6     .04       0
  5030.8     .08       0
#XS Ineff= 2 , 0
       0  4759.4    42.7  5081.8       0    43.2
Permanent Ineff=
       F       F
Bank Sta=4943.6,5030.8
XS Rating Curve= 0 ,0
Exp/Cntr=0.3,0.1

Type RM Length L Ch R = 1 ,2864.6  ,485.9,493.9,478.6
BEGIN DESCRIPTION:
Cross Section 2864.6
END DESCRIPTION:
XS GIS Cut Line= 5
      3119571.08     13800645.91      3118809.37     13800245.42
       3118298.1     13800204.52      3117745.92     13800173.84
      3117380.96     13800169.74
#Sta/Elev= 30
  3266.8   42.39  3416.8   41.75  3486.8   40.81  3501.8   41.77  3556.8   42.15
  3601.8   41.54  3726.8   41.49  3776.8   40.36  3811.8   41.68  3921.8   41.33
  3946.8   40.59  4127.4    41.9  4267.4   40.66  4640.3   42.41  4755.3   41.35
  4775.3   40.15  4820.3   41.22  4840.3   42.36  4911.2    42.8  4934.8   42.49
  4948.8   41.26  4955.9   38.45  4999.8   28.35  5020.1   35.27  5026.7   39.53
  5033.1   41.81  5193.3   43.33  5258.3   42.97  5288.3   43.56  5558.3   43.92
#Mann= 4 , 1 , 0
  3266.8      .1       0  4911.2     .08       0  4948.8     .04       0
  5033.1     .08       0
Bank Sta=4948.8,5033.1
XS Rating Curve= 0 ,0
Exp/Cntr=0.3,0.1

Type RM Length L Ch R = 1 ,2370.7  ,322.1,379.6,428.9
BEGIN DESCRIPTION:
Cross Section 2370.7-Interpolated
END DESCRIPTION:
XS GIS Cut Line= 4
      3120106.15     13800183.21      3119844.26     13799856.72
      3117957.88     13799691.15      3116256.98     13799675.45
#Sta/Elev= 30
  2689.1    42.2  2815.7   41.38  2987.8    40.3  3284.3   40.61  3441.2   42.02
  3486.4   39.57  3606.8   41.82  3851.8   39.84  3934.9   40.85  3998.3   39.32
  4088.7   40.78  4254.3   40.84  4404.1   39.34  4419.4   40.41  4433.2   39.36
  4474.8   40.58  4510.3   39.97  4557.8   41.57  4640.9   41.86  4675.9    39.6
  4751.6   41.48  4922.7    41.9  4948.8   40.91  4955.9    38.1  4999.8      28
  5020.1   34.92  5026.7   39.18  5033.1   41.46  5052.2   42.64  6702.3   43.65
#Mann= 5 , 1 , 0
  2689.1      .2       0  2815.7      .1       0  4922.7     .08       0
  4948.8     .03       0  5033.1     .08       0
Bank Sta=4948.8,5033.1
XS Rating Curve= 0 ,0
Exp/Cntr=0.5,0.3

Type RM Length L Ch R = 1 ,1991.1  ,120.6,241.8,231.7
BEGIN DESCRIPTION:
Upstream Section of Bridge/Culvert/Weir
END DESCRIPTION:
XS GIS Cut Line= 6
      3120217.21     13799599.09      3118699.86     13799514.02
      3118060.68     13799493.13      3117864.33     13799476.42
      3117517.59     13799459.71      3116487.95     13799400.41
#Sta/Elev= 30
  3025.7   42.51  3199.8   41.76  3773.4   41.32  3847.9   39.53  3882.9   41.35
  3927.9   41.81  4724.5   41.82  4754.5    41.7  4784.5   39.41  4814.5   39.35
  4840.1   41.64 4879.16   42.29 4893.24   39.09 4918.41   39.17 4932.42   42.19
 4985.86   40.47 4990.39   28.54  4998.7    27.6 5009.67   28.09 5011.97   38.54
 5046.69    40.2 5081.28   42.17  5122.2   42.63  5264.5   41.93  5294.5   39.58
  5309.5   35.78  5339.5   40.02  5354.8   40.67  5695.5   42.27  6760.5   43.22
#Mann= 5 , 1 , 0
  3025.7      .2       0  3199.8      .1       0 4985.86    .025       0
 5046.69      .1       0  5354.8     .08       0
#XS Ineff= 2 , 0
       0    4963   40.42    5057       0    40.3
Permanent Ineff=
       F       F
Bank Sta=4985.86,5046.69
XS Rating Curve= 0 ,0
Exp/Cntr=0.5,0.3

Type RM Length L Ch R = 2 ,1870.2  ,,,
BEGIN DESCRIPTION:
AIRPORT BOULEVARD - 52 degree skew
Structure ID: C32-03
END DESCRIPTION:
Bridge Culvert--1,0,-1,-1, 0
Deck Dist Width WeirC Skew NumUp NumDn MinLoCord MaxHiCord MaxSubmerge Is_Ogee
10,221.8,3,0, 60, 60, , , 0.95, 0, 1,1,,
  3025.7  3095.7  3428.4  3548.4  3573.4  3608.4  3773.4  3802.9  3817.9  3847.9
  3882.9  3927.9  4120.6  4310.6  4350.6  4440.6  4455.6  4605.6  4620.6  4724.5
  4754.5  4769.5  4784.5  4814.5  4840.1 4879.16 4891.07 4891.25 4893.05 4893.24
 4918.41 4918.66  4923.8 4932.42 4977.87 4978.59  4978.7 4985.86 4990.39  4998.7
 5009.67 5011.97 5025.01 5025.12 5046.69 5081.28  5122.2  5264.5  5279.5  5294.5
  5309.5  5324.5  5339.5  5354.5  5384.5    5508  5695.5  6695.5  6745.5  6760.5
    42.5   41.66   41.94   41.52   41.12   41.86   41.31   40.11   40.44   39.52
   41.34    41.8   41.24   41.37   41.94   41.14   41.56   41.44   41.09   41.82
    41.7   41.04   41.05   41.08   41.64   42.29   41.06   40.56   40.55   40.55
   40.43   40.43   40.59   42.19   41.48   41.39   41.79    41.8   41.81   41.82
   41.84   41.85   41.83   41.13   41.02   42.17   42.63   41.93   41.31   40.36
   40.41   40.46   40.51   40.67   40.66   41.65   42.26   43.27   42.92   43.21
    42.5   41.66   41.94   41.52   41.12   41.86   41.31   40.11   40.44   39.52
   41.34    41.8   41.24   41.37   41.94   41.14   41.56   41.43   41.08   41.81
   41.69   40.87    39.4   39.34   41.63   42.28   40.07   40.03    39.7   39.08
   39.16   39.63   40.58   42.18   41.47   41.38   41.37   40.46   28.53   27.59
   28.08   38.53   39.15   39.16   40.19   42.16   42.62   41.92    41.3   39.57
   35.77   37.15   40.01   40.66   40.39   41.65   42.26   43.27   42.92   43.21
  3025.7  3095.7  3428.4  3548.4  3573.4  3608.4  3773.4  3802.9  3817.9  3847.9
  3882.9  3927.9  4120.6  4310.6  4350.6  4440.6  4455.6  4605.6  4620.6  4724.5
  4754.5  4769.5  4784.5  4814.5  4840.1 4879.16 4891.07 4891.25 4893.05 4893.24
 4918.41 4918.66  4923.8 4932.42 4977.87 4978.59  4978.7 4985.86 4990.39  4998.7
 5009.67 5011.97 5025.01 5025.12 5046.69 5081.28  5122.2  5264.5  5279.5  5294.5
  5309.5  5324.5  5339.5  5354.5  5384.5    5508  5695.5  6695.5  6745.5  6760.5
    42.5   41.66   41.94   41.52   41.12   41.86   41.31   40.11   40.44   39.52
   41.34    41.8   41.24   41.37   41.94   41.14   41.56   41.44   41.09   41.82
    41.7   41.04   41.05   41.08   41.64   42.29   41.06   40.56   40.55   40.55
   40.43   40.43   40.59   42.19   41.48   41.39   41.79    41.8   41.81   41.82
   41.84   41.85   41.83   41.13   41.02   42.17   42.63   41.93   41.31   40.36
   40.41   40.46   40.51   40.67   40.66   41.65   42.26   43.27   42.92   43.21
   42.05   41.21   41.49   41.07   40.67   41.41   40.86   39.66   39.99   39.07
   40.89   41.35   40.79   40.92   41.49   40.69   41.11   40.98   40.63   41.36
   41.24   40.42   38.95   38.89   41.18   41.83   39.62   39.58   39.25   38.63
   38.71   39.18   40.13   41.73   41.02   40.93   40.92   40.01   28.08   27.14
   27.63   38.08    38.7   38.71   39.74   41.71   42.17   41.47   40.85   39.12
   35.32    36.7   39.56   40.21   39.94    41.2   41.81   42.82   42.47   42.76
BR Coef= 1 , 0 , 0 ,1.25, 0 ,,,0.8,-1,2,0,
WSPro=,,,, 1 ,,,, 0 ,,,, 0 ,,,,-1 ,-1 ,-1 , 0 , 0 , 0 , 0 , 0
Culvert=2,10,10,221.8,0.015,0.4,1,8,1,27.68,4994.7,26.81,4994.7,Culvert #1  , 0 ,10
Culvert Bottom n=0.015
Culvert=2,10,10,221.8,0.015,0.4,1,8,1,27.82,5005.5,27.17,5005.5,Culvert #2  , 0 ,10
Culvert Bottom n=0.015
BR U #Sta/Elev= 82
  3025.7    42.5  3095.7   41.66  3199.8   41.75  3428.4   41.94  3548.4   41.52
  3573.4   41.12  3608.4   41.86  3773.4   41.31  3787.9   40.85  3802.9   40.11
  3817.9   40.44  3832.9   40.06  3847.9   39.52  3852.9   39.65  3862.9   40.45
  3882.9   41.34  3927.9    41.8  4120.6   41.24  4310.6   41.37  4350.6   41.94
  4440.6   41.14  4455.6   41.56  4545.5   41.48  4605.6   41.43  4620.6   41.08
  4724.5   41.81  4754.5   41.69  4769.5   40.87  4784.5    39.4  4814.5   39.34
 4839.23   41.55  4840.1   41.63 4879.16   42.28 4891.07   40.07 4891.25   40.03
 4893.05    39.7 4893.24   39.08 4918.41   39.16 4918.66   39.63  4923.8   40.58
 4924.05   40.63 4932.42   42.18 4960.57   41.74 4975.39   41.51 4977.87   41.47
 4978.59   41.38  4978.7   41.37  4978.8   41.35 4985.86   40.46 4990.39   28.53
  4998.7   27.59 5009.67   28.08 5011.97   38.53 5019.41   38.89  5024.9   39.15
 5025.01   39.15 5025.12   39.16 5040.92   39.91 5046.69   40.19 5078.74   42.02
 5081.28   42.16  5122.2   42.62 5128.77   42.57 5171.37   42.23 5184.39    42.1
    5185   42.09  5190.4   42.04  5264.5   41.92  5279.5    41.3  5294.5   39.57
  5309.5   35.77  5324.5   37.15  5339.5   40.01  5354.5   40.66  5354.8   40.66
  5384.5   40.39    5486   41.43    5508   41.65  5695.5   42.26  6695.5   43.27
  6745.5   42.92  6760.5   43.21
BR U #Mann= 5
  3025.7      .2  3199.8      .1 4985.86    .025 5046.69      .1  5354.8     .08
BR U Banks=4985.86,5046.69
BR D #Sta/Elev= 82
  3025.7   42.05  3095.7   41.21  3199.8    41.3  3428.4   41.49  3548.4   41.07
  3573.4   40.67  3608.4   41.41  3773.4   40.86  3787.9    40.4  3802.9   39.66
  3817.9   39.99  3832.9   39.61  3847.9   39.07  3852.9    39.2  3862.9      40
  3882.9   40.89  3927.9   41.35  4120.6   40.79  4310.6   40.92  4350.6   41.49
  4440.6   40.69  4455.6   41.11  4545.5   41.03  4605.6   40.98  4620.6   40.63
  4724.5   41.36  4754.5   41.24  4769.5   40.42  4784.5   38.95  4814.5   38.89
 4839.23    41.1  4840.1   41.18 4879.16   41.83 4891.07   39.62 4891.25   39.58
 4893.05   39.25 4893.24   38.63 4918.41   38.71 4918.66   39.18  4923.8   40.13
 4924.05   40.18 4932.42   41.73 4960.57   41.29 4975.39   41.06 4977.87   41.02
 4978.59   40.93  4978.7   40.92  4978.8    40.9 4985.86   40.01 4990.39   28.08
  4998.7   27.14 5009.67   27.63 5011.97   38.08 5019.41   38.44  5024.9    38.7
 5025.01    38.7 5025.12   38.71 5040.92   39.46 5046.69   39.74 5078.74   41.57
 5081.28   41.71  5122.2   42.17 5128.77   42.12 5171.37   41.78 5184.39   41.65
    5185   41.64  5190.4   41.59  5264.5   41.47  5279.5   40.85  5294.5   39.12
  5309.5   35.32  5324.5    36.7  5339.5   39.56  5354.5   40.21  5354.8   40.21
  5384.5   39.94    5486   40.98    5508    41.2  5695.5   41.81  6695.5   42.82
  6745.5   42.47  6760.5   42.76
BR D #Mann= 5
  3025.7      .2  3199.8      .1 4985.86    .025 5046.69      .1  5354.8     .08
BR D Banks=4985.86,5046.69
BC Design=,, 0 ,, 0 ,,,,,,
BC HTab HWMax=43.28
BC Use User HTab Curves=0
BC User HTab FreeFlow(D)= 0

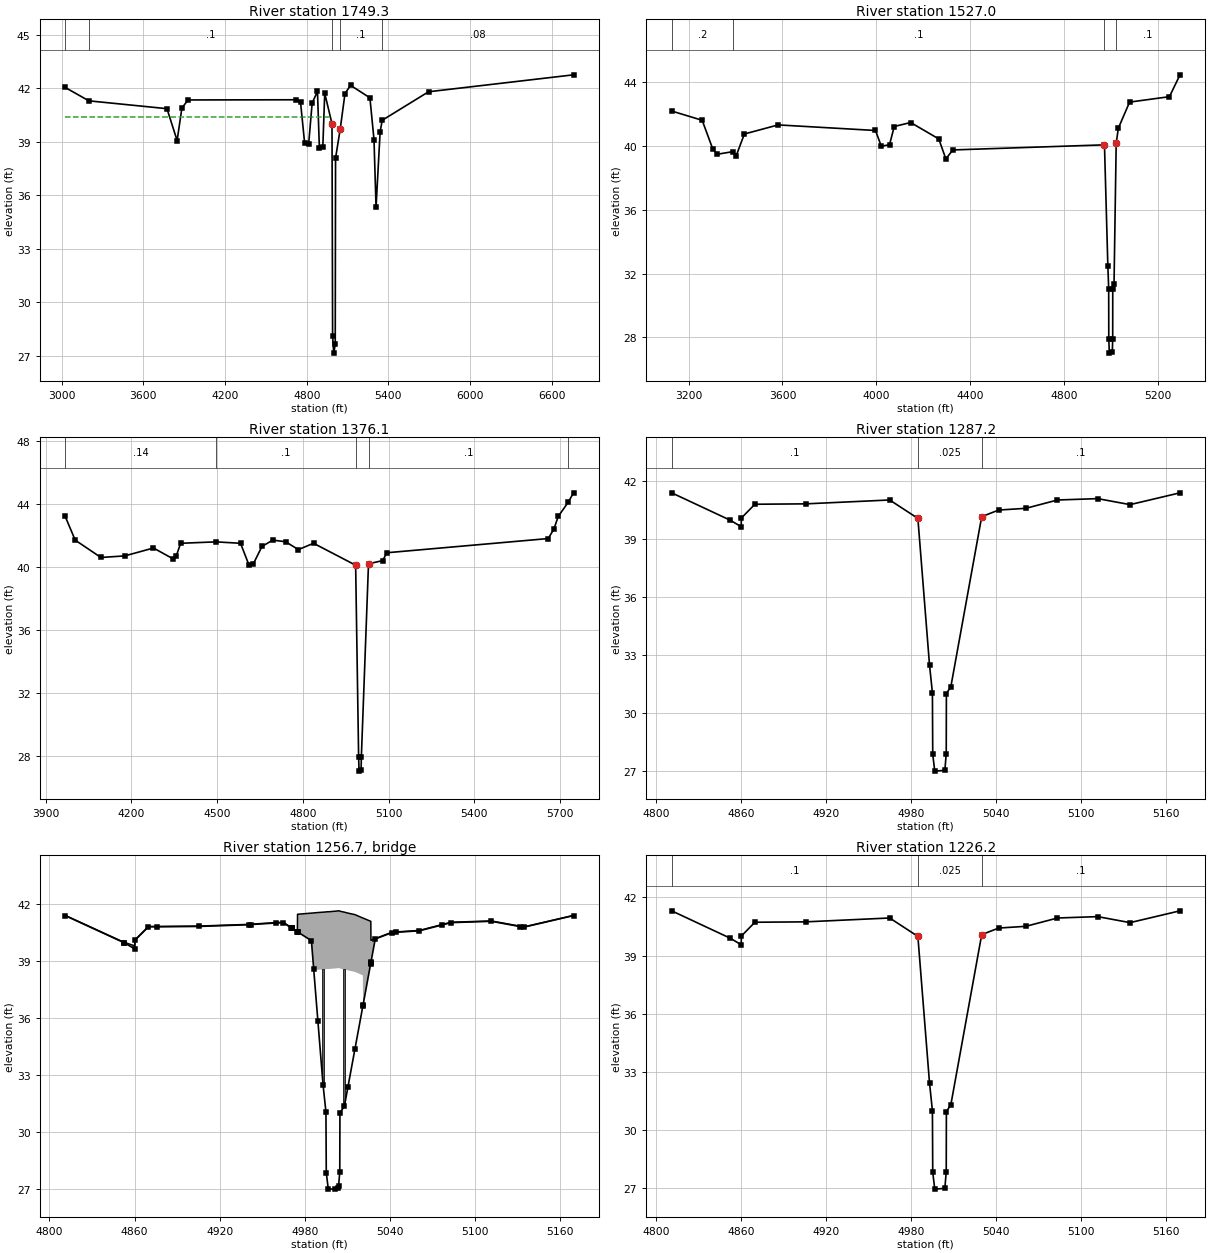
Type RM Length L Ch R = 1 ,1749.3  ,191.6,222.3,286.7
BEGIN DESCRIPTION:
Downstream Section of Bridge/Culvert/Weir
END DESCRIPTION:
XS GIS Cut Line= 6
      3120428.05     13799480.73       3118910.7     13799395.66
      3118271.52     13799374.77      3118075.17     13799358.06
      3117728.43     13799341.35       3116698.8     13799282.05
#Sta/Elev= 30
  3025.7   42.05  3199.8    41.3  3773.4   40.86  3847.9   39.07  3882.9   40.89
  3927.9   41.35  4724.5   41.36  4754.5   41.24  4784.5   38.95  4814.5   38.89
  4840.1   41.18 4879.16   41.83 4893.24   38.63 4918.41   38.71 4932.42   41.73
 4985.86   40.01 4990.39   28.08  4998.7   27.14 5009.67   27.63 5011.97   38.08
 5046.69   39.74 5081.28   41.71  5122.2   42.17  5264.5   41.47  5294.5   39.12
  5309.5   35.32  5339.5   39.56  5354.8   40.21  5695.5   41.81  6760.5   42.76
#Mann= 5 , 1 , 0
  3025.7      .2       0  3199.8      .1       0 4985.86    .025       0
 5046.69      .1       0  5354.8     .08       0
#XS Ineff= 2 , 0
       0    4976   40.42    5057       0    40.3
Permanent Ineff=
       F       F
Bank Sta=4985.86,5046.69
XS Rating Curve= 0 ,0
Exp/Cntr=0.5,0.3

Type RM Length L Ch R = 1 ,1527.0  ,269.9,150.9,65.4
BEGIN DESCRIPTION:
Cross Section 1527.0-Interpolated
END DESCRIPTION:
XS GIS Cut Line= 4
      3120519.43      13799428.9       3118769.7      13799333.7
       3118615.3      13799202.8      3118405.57     13799239.76
#Sta/Elev= 30
  3127.7    42.2  3257.7   41.62  3302.7   39.83  3322.7   39.49  3390.8   39.66
  3402.7   39.39  3437.7   40.76  3581.8   41.33  3996.8   40.98  4021.8   39.99
  4056.8   40.09  4076.8   41.23  4146.8   41.48  4266.8   40.45  4296.8    39.2
  4326.8   39.76  4973.3   40.08  4987.7   32.51  4991.3   31.07  4991.7   27.89
  4994.2   27.02  5006.7   27.06  5008.4   27.92  5008.6   31.03  5014.1   31.38
  5023.3   40.17  5032.4   41.12  5080.4   42.76  5250.4    43.1  5295.4   44.47
#Mann= 4 , 1 , 0
  3127.7      .2       0  3390.8      .1       0  4973.3    .025       0
  5023.3      .1       0
Bank Sta=4973.3,5023.3
XS Rating Curve= 0 ,0
Exp/Cntr=0.3,0.1

Type RM Length L Ch R = 1 ,1376.1  ,71,88.9,76.7
BEGIN DESCRIPTION:
Cross Section 1376.1-Interpolated
END DESCRIPTION:
XS GIS Cut Line= 6
      3119764.49      13799250.2      3119515.39     13799335.19
      3119099.37     13799301.97      3119011.65     13799188.99
      3118396.25     13799154.43      3118088.71     13799282.58
#Sta/Elev= 30
    3968    43.2    4003    41.7    4093    40.6  4176.5    40.7    4277    41.2
    4347    40.5    4357    40.7    4372    41.5  4495.6   41.59  4581.8    41.5
  4611.8    40.1  4626.8    40.2  4656.8    41.3  4694.4    41.7  4739.4    41.6
  4784.4    41.1  4837.4    41.5 4984.78   40.11 4995.27   27.92 4996.69   27.05
 5003.82   27.09 5004.79   27.95 5029.81    40.2  5079.2    40.4  5094.2    40.9
  5658.9    41.8  5678.9    42.4  5693.9    43.2  5728.8    44.1  5747.6    44.7
#Mann= 5 , 1 , 0
    3968     .14       0  4495.6      .1       0 4984.78    .025       0
 5029.81      .1       0  5728.8      .2       0
Bank Sta=4984.78,5029.81
XS Rating Curve= 0 ,0
Exp/Cntr=0.5,0.3

Type RM Length L Ch R = 1 ,1287.2  ,60.6,61,62.9
BEGIN DESCRIPTION:
Upstream Section of Bridge/Culvert/Weir
END DESCRIPTION:
XS GIS Cut Line= 5
      3119058.46     13799183.67      3119036.09     13799135.45
       3118951.8     13799133.04      3118794.34     13799127.12
      3118730.86     13799123.97
#Sta/Elev= 23
  4811.1   41.39 4852.54   39.97 4860.12   39.64 4860.29   40.09 4869.81    40.8
 4905.61   40.82 4964.89   41.02 4984.78   40.07 4992.99    32.5 4995.04   31.06
 4995.27   27.88 4996.69   27.01 5003.82   27.05 5004.79   27.91  5004.9   31.02
 5008.04   31.37 5029.81   40.16 5041.78    40.5 5060.99   40.59 5083.28   41.02
 5111.66   41.09 5134.46   40.78  5169.7   41.39
#Mann= 3 , 1 , 0
  4811.1      .1       0 4984.78    .025       0 5029.81      .1       0
#XS Ineff= 2 , 0
       0    4976   39.81    5031       0   40.09
Permanent Ineff=
       F       F
Bank Sta=4984.78,5029.81
XS Rating Curve= 0 ,0
Exp/Cntr=0.5,0.3

Type RM Length L Ch R = 3 ,1256.7  ,,,
BEGIN DESCRIPTION:
AKARD STREET - 55 degree skew
Structure ID: C32-2
END DESCRIPTION:
Bridge Culvert--1,0,-1,-1, 0
Deck Dist Width WeirC Skew NumUp NumDn MinLoCord MaxHiCord MaxSubmerge Is_Ogee
10,41,2.6,0, 49, 49, , , 0.95, 0, 1,1,,
  4811.1 4852.43 4852.54 4860.12 4860.29 4869.81 4875.51 4905.61 4940.95 4942.37
 4959.47 4964.89 4970.65 4970.79  4970.9 4970.99 4974.89 4974.99  4975.1 4984.78
 4986.38 4989.34 4992.99 4995.04 4995.27 4996.69 5001.48 5003.82 5003.93 5004.79
  5004.9 5008.04  5010.6  5015.5 5021.09  5021.2 5026.58 5026.69  5026.8 5029.81
 5041.78 5044.12 5060.99 5077.06 5083.28 5111.66 5132.24 5134.46  5169.7
    41.4   39.99   39.99    39.8   40.11   40.82   40.82   40.84   40.93   40.94
   41.02   41.04   40.76   40.76   40.75   40.75   40.56   41.46   41.46   41.52
   41.53   41.55   41.57   41.58   41.59   41.59   41.62   41.64   41.64   41.63
   41.62   41.57   41.52   41.44   41.26   41.26   41.09   41.09   40.09   40.18
   40.52   40.53   40.61   40.92   41.04   41.11   40.83   40.79    41.4
   41.39   39.97   39.97   39.64   40.09    40.8    40.8   40.82   40.91   40.92
      41   41.02   40.74   40.74   40.73   40.73   40.54   40.54   40.53   40.07
   38.59   38.54   38.56   38.57   38.58   38.58   38.61   38.63   38.63   38.62
   38.61   38.56   38.51   38.43   38.25   36.68   38.86    38.9   38.94   40.16
    40.5   40.51   40.59    40.9   41.02   41.09   40.81   40.78   41.39
  4811.1 4852.43 4852.54 4860.12 4860.29 4869.81 4875.51 4905.61 4940.95 4942.37
 4959.47 4964.89 4970.65 4970.79  4970.9 4970.99 4974.89 4974.99  4975.1 4984.78
 4986.38 4989.34 4992.99 4995.04 4995.27 4996.69 5001.48 5003.82 5003.93 5004.79
  5004.9 5008.04  5010.6  5015.5 5021.09  5021.2 5026.58 5026.69  5026.8 5029.81
 5041.78 5044.12 5060.99 5077.06 5083.28 5111.66 5132.24 5134.46  5169.7
    41.4   39.99   39.99    39.8   40.11   40.82   40.82   40.84   40.93   40.94
   41.02   41.04   40.76   40.76   40.75   40.75   40.56   41.46   41.46   41.52
   41.53   41.55   41.57   41.58   41.59   41.59   41.62   41.64   41.64   41.63
   41.62   41.57   41.52   41.44   41.26   41.26   41.09   41.09   40.09   40.18
   40.52   40.53   40.61   40.92   41.04   41.11   40.83   40.79    41.4
    41.3   39.88   39.88   39.55      40   40.71   40.71   40.73   40.82   40.83
   40.91   40.93   40.65   40.65   40.64   40.64   40.45   40.45   40.44   39.98
    38.5   38.45   38.47   38.48   38.49   38.49   38.52   38.54   38.54   38.53
   38.52   38.47   38.42   38.34   38.16   36.59   38.77   38.81   38.85   40.07
   40.41   40.42    40.5   40.81   40.93      41   40.72   40.69    41.3
Pier Skew, UpSta & Num, DnSta & Num=  ,4993, 2 ,4993, 2 , 0 , 0 , 0 ,,
     1.3     1.3
   31.04   39.56
     1.3     1.3
   30.95   39.47
Pier Skew, UpSta & Num, DnSta & Num=  ,5008, 2 ,5008, 2 , 0 , 0 , 0 ,,
     1.3     1.3
    30.3   39.57
     1.3     1.3
   30.21   39.48
Abutment Skew #Up #Dn= , 2 , 2
 4970.79 4989.34
   40.73   35.86
 4970.79 4989.34
   40.64   35.77
Abutment Skew #Up #Dn= , 2 , 2
  5010.6 5021.29
    32.4   38.25
  5010.6 5021.29
   32.31   38.16
BR Coef= 1 , 1 , 0 ,1.25, 0 ,,,0.8,0,2,0,
WSPro=,,,, 1 ,,,, 0 ,,,, 0 ,,,,-1 ,-1 ,-1 , 0 , 0 , 0 , 0 , 0
BR U #Sta/Elev= 49
  4811.1   41.39 4852.43   39.97 4852.54   39.97 4860.12   39.64 4860.29   40.09
 4869.81    40.8 4875.51    40.8 4905.61   40.82 4940.95   40.91 4942.37   40.92
 4959.47      41 4964.89   41.02 4970.65   40.74 4970.79   40.74  4970.9   40.73
 4970.99   40.73 4974.89   40.54 4974.99   40.54  4975.1   40.53 4984.78   40.07
 4986.38   38.59 4989.34   35.86 4992.99    32.5 4995.04   31.06 4995.27   27.88
 4996.69   27.01 5001.48   27.02 5003.82   27.05 5003.93   27.15 5004.79   27.91
  5004.9   31.02 5008.04   31.37  5010.6    32.4  5015.5   34.38 5021.09   36.64
  5021.2   36.68 5026.58   38.86 5026.69    38.9  5026.8   38.94 5029.81   40.16
 5041.78    40.5 5044.12   40.51 5060.99   40.59 5077.06    40.9 5083.28   41.02
 5111.66   41.09 5132.24   40.81 5134.46   40.78  5169.7   41.39
BR U #Mann= 3
  4811.1      .1 4984.78    .025 5029.81      .1
BR U Banks=4984.78,5029.81
BR D #Sta/Elev= 49
  4811.1    41.3 4852.43   39.88 4852.54   39.88 4860.12   39.55 4860.29      40
 4869.81   40.71 4875.51   40.71 4905.61   40.73 4940.95   40.82 4942.37   40.83
 4959.47   40.91 4964.89   40.93 4970.65   40.65 4970.79   40.65  4970.9   40.64
 4970.99   40.64 4974.89   40.45 4974.99   40.45  4975.1   40.44 4984.78   39.98
 4986.38    38.5 4989.34   35.77 4992.99   32.41 4995.04   30.97 4995.27   27.79
 4996.69   26.92 5001.48   26.93 5003.82   26.96 5003.93   27.06 5004.79   27.82
  5004.9   30.93 5008.04   31.28  5010.6   32.31  5015.5   34.29 5021.09   36.55
  5021.2   36.59 5026.58   38.77 5026.69   38.81  5026.8   38.85 5029.81   40.07
 5041.78   40.41 5044.12   40.42 5060.99    40.5 5077.06   40.81 5083.28   40.93
 5111.66      41 5132.24   40.72 5134.46   40.69  5169.7    41.3
BR D #Mann= 3
  4811.1      .1 4984.78    .025 5029.81      .1
BR D Banks=4984.78,5029.81
BC Design=,, 0 ,, 0 ,,,,,,
BC HTab HWMax=41.39
BC Use User HTab Curves=0
BC User HTab FreeFlow(D)= 0

Type RM Length L Ch R = 1 ,1226.2  ,110.7,207.9,305.7
BEGIN DESCRIPTION:
Downstream Section of Bridge/Culvert/Weir
END DESCRIPTION:
XS GIS Cut Line= 5
      3119111.63     13799153.76      3119089.25     13799105.55
      3119004.96     13799103.14       3118847.5     13799097.22
      3118784.03     13799094.06
#Sta/Elev= 23
  4811.1   41.31 4852.54   39.89 4860.12   39.56 4860.29   40.01 4869.81   40.72
 4905.61   40.74 4964.89   40.94 4984.78   39.99 4992.99   32.42 4995.04   30.98
 4995.27    27.8 4996.69   26.93 5003.82   26.97 5004.79   27.83  5004.9   30.94
 5008.04   31.29 5029.81   40.08 5041.78   40.42 5060.99   40.51 5083.28   40.94
 5111.66   41.01 5134.46    40.7  5169.7   41.31
#Mann= 3 , 1 , 0
  4811.1      .1       0 4984.78    .025       0 5029.81      .1       0
#XS Ineff= 2 , 0
       0    4976   39.81    5031       0   40.09
Permanent Ineff=
       F       F
Bank Sta=4984.78,5029.81
XS Rating Curve= 0 ,0
Exp/Cntr=0.5,0.3

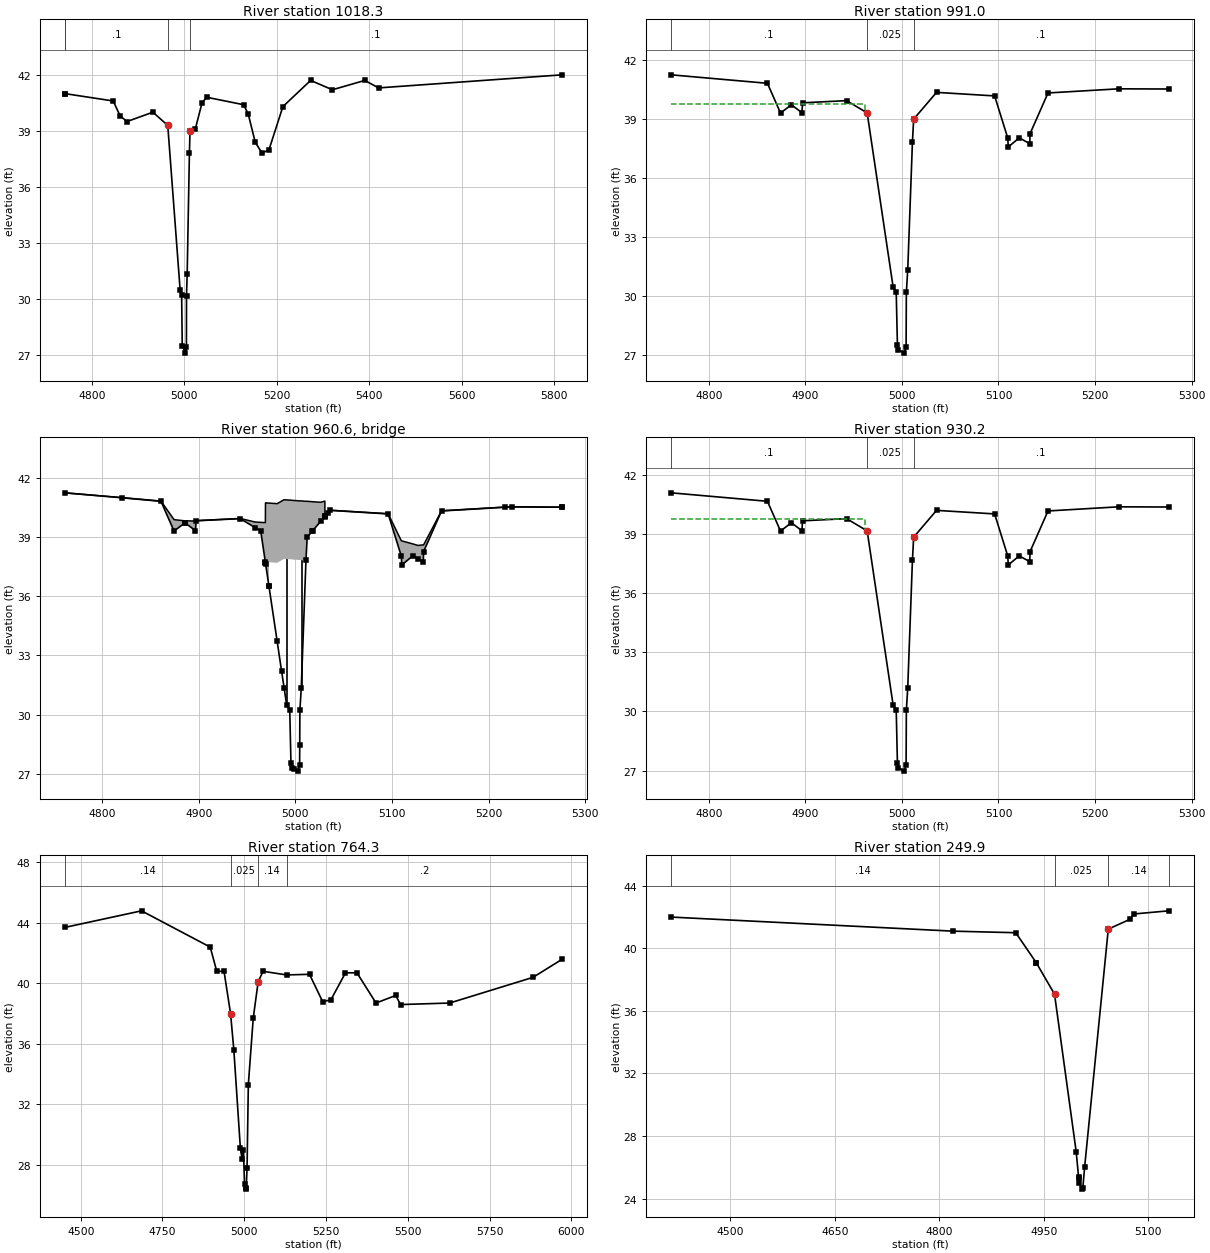
Type RM Length L Ch R = 1 ,1018.3  ,10.5,27.3,34.2
BEGIN DESCRIPTION:
Cross Section 1018.3-Interpolated
END DESCRIPTION:
XS GIS Cut Line= 6
      3119130.89     13799261.37      3119143.77     13799070.86
      3119109.01     13798970.46       3119120.6     13798688.55
      3119035.64     13798611.32      3118653.33     13798617.76
#Sta/Elev= 30
    4741      41  4742.6   40.99    4846    40.6    4861    39.8    4876    39.5
  4931.9      40 4964.05   39.29 4990.84   30.48 4994.12    30.2 4995.38    27.5
 5002.35    27.1 5004.45   27.41 5004.62   30.18 5006.05   31.32 5010.92   37.81
 5012.18   38.97  5023.7    39.1  5038.2    40.5  5048.2    40.8  5128.2    40.4
  5138.2    39.9  5153.2    38.4  5168.2    37.8  5183.2      38  5213.2    40.3
  5273.2    41.7  5320.3    41.2  5390.3    41.7  5420.3    41.3  5817.5      42
#Mann= 4 , 1 , 0
    4741      .2       0  4742.6      .1       0 4964.05    .025       0
 5012.18      .1       0
Bank Sta=4964.05,5012.18
XS Rating Curve= 0 ,0
Exp/Cntr=0.5,0.3

Type RM Length L Ch R = 1 ,991.0   ,59.5,60.8,61.3
BEGIN DESCRIPTION:
Upstream Section of Bridge/Culvert/Weir
END DESCRIPTION:
XS GIS Cut Line= 3
      3119148.81      13799222.8      3119163.37     13798942.94
      3119173.17     13798708.29
#Sta/Elev= 28
  4761.1   41.24 4860.81   40.81 4874.34    39.3 4885.59   39.72 4896.51   39.32
 4897.18   39.82 4942.71   39.93 4964.05   39.31 4990.84    30.5 4994.12   30.22
 4995.38   27.52 4996.39   27.29 5002.35   27.12 5004.35   27.43 5004.62    30.2
 5006.05   31.34 5010.92   37.83 5012.18   38.99 5035.87   40.35 5096.01   40.17
 5109.62   38.03 5110.12   37.58 5121.46   38.04 5132.38   37.75 5132.72   38.26
 5151.28   40.32 5224.36   40.53 5276.19   40.52
#Mann= 3 , 1 , 0
  4761.1      .1       0 4964.05    .025       0 5012.18      .1       0
#XS Ineff= 2 , 0
       0    4962   39.74    5021       0   38.57
Permanent Ineff=
       F       F
Bank Sta=4964.05,5012.18
XS Rating Curve= 0 ,0
Exp/Cntr=0.5,0.3

Type RM Length L Ch R = 3 ,960.6   ,,,
BEGIN DESCRIPTION:
DULCIMER ROAD - 33 degree skew
Structure ID: C32-1
END DESCRIPTION:
Bridge Culvert--1,0,-1,-1, 0
Deck Dist Width WeirC Skew NumUp NumDn MinLoCord MaxHiCord MaxSubmerge Is_Ogee
10,40.8,2.6,0, 51, 51, , , 0.95, 0, 1,1,,
  4761.1 4819.99 4860.81 4874.34 4885.17 4885.59 4896.51 4897.18 4942.71 4958.17
 4964.05 4968.88 4968.99  4969.1 4972.53 4972.62 4981.02 4985.72 4988.24 4990.84
 4994.12 4995.38 4996.39 4998.74 5002.35 5004.35 5004.45 5004.62 5006.05 5010.92
 5012.18 5017.61 5017.72 5026.12 5030.37 5030.48 5030.58 5033.43 5035.87 5096.01
 5109.62 5110.12 5121.46 5126.92 5132.38 5132.72 5151.28 5217.39 5224.36 5276.11
 5276.19
   41.25   41.01   40.83   39.89   39.83   39.83   39.82   39.84   39.95   39.77
   39.75   39.74   40.74   40.74   40.73   40.73    40.7   40.83    40.9   40.89
   40.88   40.88   40.87   40.86   40.85   40.84   40.84   40.84   40.84   40.82
   40.82    40.8    40.8   40.77   40.83   40.83   40.07   40.23   40.37   40.19
   38.82   38.81   38.66   38.58   38.61   38.61   40.34   40.53   40.54   40.52
   40.53
   41.25      41   40.82   39.31   39.71   39.73   39.33   39.83   39.94   39.49
   39.32   37.73    37.7   37.66   36.53   37.73    37.7   37.83    37.9   37.89
   37.88   37.88   37.87   37.86   37.85   37.84   37.84   37.84   37.84   37.84
      39   39.31   39.32    39.8   40.04   40.05   40.06   40.22   40.36   40.18
   38.04   37.59   38.05    37.9   37.76   38.27   40.33   40.52   40.54   40.52
   40.53
  4761.1 4819.99 4860.81 4874.34 4885.17 4885.59 4896.51 4897.18 4942.71 4958.17
 4964.05 4968.88 4968.99  4969.1 4972.53 4972.62 4981.02 4985.72 4988.24 4990.84
 4994.12 4995.38 4996.39 4998.74 5002.35 5004.35 5004.45 5004.62 5006.05 5010.92
 5012.18 5017.61 5017.72 5026.12 5030.37 5030.48 5030.58 5033.43 5035.87 5096.01
 5109.62 5110.12 5121.46 5126.92 5132.38 5132.72 5151.28 5217.39 5224.36 5276.11
 5276.19
   41.25   41.01   40.83   39.89   39.83   39.83   39.82   39.84   39.95   39.77
   39.75   39.74   40.74   40.74   40.73   40.73    40.7   40.83    40.9   40.89
   40.88   40.88   40.87   40.86   40.85   40.84   40.84   40.84   40.84   40.82
   40.82    40.8    40.8   40.77   40.83   40.83   40.07   40.23   40.37   40.19
   38.82   38.81   38.66   38.58   38.61   38.61   40.34   40.53   40.54   40.52
   40.53
   41.12   40.87   40.69   39.18   39.58    39.6    39.2    39.7   39.81   39.36
   39.19    37.6   37.57   37.53    36.4    37.6   37.57    37.7   37.77   37.76
   37.75   37.75   37.74   37.73   37.72   37.71   37.71   37.71   37.71   37.71
   38.87   39.18   39.19   39.67   39.91   39.92   39.93   40.09   40.23   40.05
   37.91   37.46   37.92   37.77   37.63   38.14    40.2   40.39   40.41   40.39
    40.4
Pier Skew, UpSta & Num, DnSta & Num=  ,4990.8, 2 ,4990.8, 2 , 0 , 0 , 0 ,,
     1.3     1.3
   29.45   38.89
     1.3     1.3
   29.32   38.76
Pier Skew, UpSta & Num, DnSta & Num=  ,5006, 2 ,5006, 2 , 0 , 0 , 0 ,,
     1.3     1.3
   29.83   38.84
     1.3     1.3
    29.7   38.71
Abutment Skew #Up #Dn= , 2 , 2
 4972.42 4981.02
   37.73   33.74
 4972.42 4981.02
    37.6   33.61
Abutment Skew #Up #Dn= , 2 , 2
 5004.45 5017.81
   28.49   39.31
 5004.45 5017.81
   28.36   39.18
BR Coef= 1 , 1 , 0 ,1.25, 0 ,,,0.8,0,2,0,
WSPro=,,,, 1 ,,,, 0 ,,,, 0 ,,,,-1 ,-1 ,-1 , 0 , 0 , 0 , 0 , 0
BR U #Sta/Elev= 51
  4761.1   41.25 4819.99      41 4860.81   40.82 4874.34   39.31 4885.17   39.71
 4885.59   39.73 4896.51   39.33 4897.18   39.83 4942.71   39.94 4958.17   39.49
 4964.05   39.32 4968.88   37.73 4968.99    37.7  4969.1   37.66 4972.53   36.53
 4972.62    36.5 4981.02   33.74 4985.72   32.19 4988.24   31.37 4990.84   30.51
 4994.12   30.23 4995.38   27.53 4996.39    27.3 4998.74   27.22 5002.35   27.13
 5004.35   27.44 5004.45   28.47 5004.62   30.21 5006.05   31.35 5010.92   37.84
 5012.18      39 5017.61   39.31 5017.72   39.32 5026.12    39.8 5030.37   40.04
 5030.48   40.05 5030.58   40.06 5033.43   40.22 5035.87   40.36 5096.01   40.18
 5109.62   38.04 5110.12   37.59 5121.46   38.05 5126.92    37.9 5132.38   37.76
 5132.72   38.27 5151.28   40.33 5217.39   40.52 5224.36   40.54 5276.11   40.52
 5276.19   40.53
BR U #Mann= 3
  4761.1      .1 4964.05    .025 5012.18      .1
BR U Banks=4964.05,5012.18
BR D #Sta/Elev= 51
  4761.1   41.12 4819.99   40.87 4860.81   40.69 4874.34   39.18 4885.17   39.58
 4885.59    39.6 4896.51    39.2 4897.18    39.7 4942.71   39.81 4958.17   39.36
 4964.05   39.19 4968.88    37.6 4968.99   37.57  4969.1   37.53 4972.53    36.4
 4972.62   36.37 4981.02   33.61 4985.72   32.06 4988.24   31.24 4990.84   30.38
 4994.12    30.1 4995.38    27.4 4996.39   27.17 4998.74   27.09 5002.35      27
 5004.35   27.31 5004.45   28.34 5004.62   30.08 5006.05   31.22 5010.92   37.71
 5012.18   38.87 5017.61   39.18 5017.72   39.19 5026.12   39.67 5030.37   39.91
 5030.48   39.92 5030.58   39.93 5033.43   40.09 5035.87   40.23 5096.01   40.05
 5109.62   37.91 5110.12   37.46 5121.46   37.92 5126.92   37.77 5132.38   37.63
 5132.72   38.14 5151.28    40.2 5217.39   40.39 5224.36   40.41 5276.11   40.39
 5276.19    40.4
BR D #Mann= 3
  4761.1      .1 4964.05    .025 5012.18      .1
BR D Banks=4964.05,5012.18
BC Design=,, 0 ,, 0 ,,,,,,
BC HTab HWMax=41.24
BC Use User HTab Curves=0
BC User HTab FreeFlow(D)= 0

Type RM Length L Ch R = 1 ,930.2   ,230.2,165.9,110.3
BEGIN DESCRIPTION:
Downstream Section of Bridge/Culvert/Weir
END DESCRIPTION:
XS GIS Cut Line= 3
      3119201.79     13799192.96      3119216.35      13798913.1
      3119226.14     13798678.45
#Sta/Elev= 28
  4761.1   41.09 4860.81   40.66 4874.34   39.15 4885.59   39.57 4896.51   39.17
 4897.18   39.67 4942.71   39.78 4964.05   39.16 4990.84   30.35 4994.12   30.07
 4995.38   27.37 4996.39   27.14 5002.35   26.97 5004.35   27.28 5004.62   30.05
 5006.05   31.19 5010.92   37.68 5012.18   38.84 5035.87    40.2 5096.01   40.02
 5109.62   37.88 5110.12   37.43 5121.46   37.89 5132.38    37.6 5132.72   38.11
 5151.28   40.17 5224.36   40.38 5276.19   40.37
#Mann= 3 , 1 , 0
  4761.1      .1       0 4964.05    .025       0 5012.18      .1       0
#XS Ineff= 2 , 0
       0    4962   39.74    5021       0    37.4
Permanent Ineff=
       F       F
Bank Sta=4964.05,5012.18
XS Rating Curve= 0 ,0
Exp/Cntr=0.5,0.3

Type RM Length L Ch R = 1 ,764.3   ,546.3,514.4,487.1
BEGIN DESCRIPTION:
Cross Section 764.3-Interpolated
END DESCRIPTION:
XS GIS Cut Line= 6
      3119775.34     13799211.93      3119576.56     13799086.69
       3119381.9     13798934.42      3119208.04     13798626.53
      3119105.99     13798557.33      3118544.99     13798560.24
#Sta/Elev= 30
    4451    43.7  4685.9    44.8  4895.9    42.4  4915.9    40.8  4938.1    40.8
  4958.1      38  4968.1    35.6  4988.1    29.1  4993.1    28.4  4997.4      29
  5000.7   26.75  5004.4   26.39    5006   26.48  5008.5   27.79  5012.4    33.3
  5027.4    37.7  5042.4    40.1  5057.4    40.8  5129.2   40.56  5199.4    40.6
  5239.4    38.8  5264.4    38.9  5309.4    40.7  5344.4    40.7  5402.7    38.7
  5462.7    39.2  5477.7    38.6  5627.7    38.7  5882.7    40.4  5971.8    41.6
#Mann= 4 , 1 , 0
    4451     .14       0  4958.1    .025       0  5042.4     .14       0
  5129.2      .2       0
Bank Sta=4958.1,5042.4
XS Rating Curve= 0 ,0
Exp/Cntr=0.3,0.1

Type RM Length L Ch R = 1 ,249.9   ,0,0,0
BEGIN DESCRIPTION:
Cross Section 249.9
END DESCRIPTION:
XS GIS Cut Line= 6
       3120116.1     13798819.58      3120114.74     13798814.85
      3119820.01     13798554.67      3119760.77     13798524.59
      3119728.69     13798510.48      3119534.06     13798419.13
#Sta/Elev= 17
  4414.8      42  4819.6    41.1  4909.6      41    4939   39.09  4939.1   39.08
  4965.3   37.07  4996.4      27  4999.9   25.35    5000   25.34  5000.7   24.96
  5004.4    24.6    5006   24.69  5008.5      26  5042.5   41.23  5073.7   41.86
  5079.6    42.2  5129.2    42.4
#Mann= 4 , 1 , 0
  4414.8     .14       0  4965.3    .025       0  5042.5     .14       0
  5129.2      .2       0
Bank Sta=4965.3,5042.5
XS Rating Curve= 0 ,0
Exp/Cntr=0.3,0.1
Stream Node=C132-00-00      ,C132-00-00_0002 , 0 , 0 ,Upstream end
Stream Node=C132-00-00      ,C132-00-00_0002 , 0 , 1 ,Downstream end

Chan Stop Cuts=-1
Use User Specified Reach Order=0
Composite Channel Slope=5